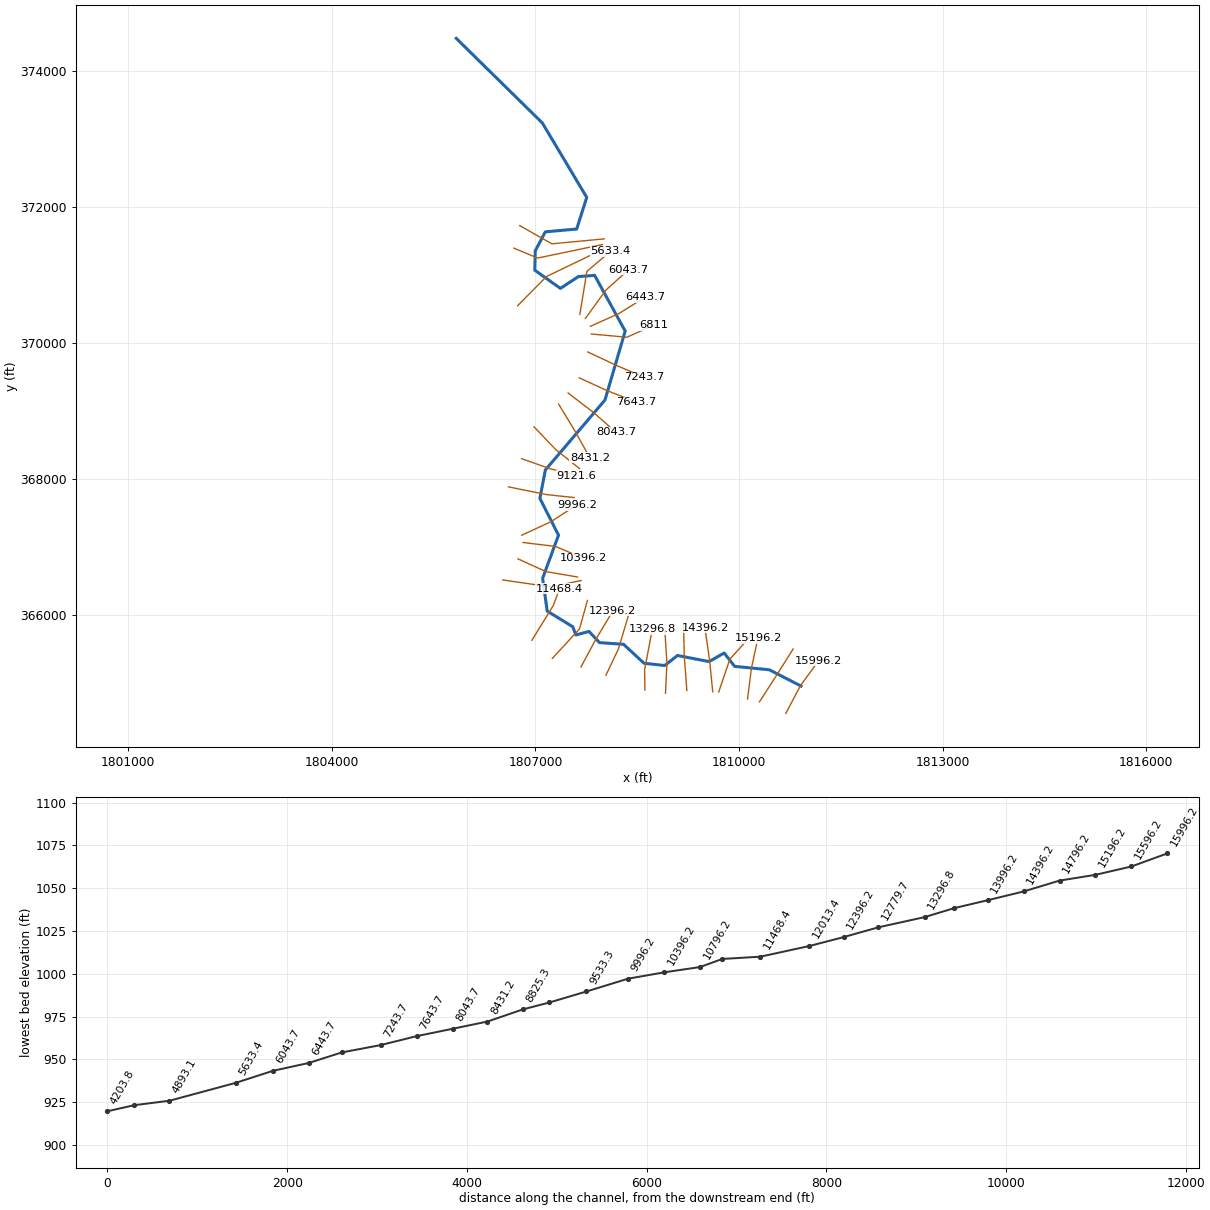
--- LttlCrk.prj (project) ---

Proj Title=LttlCrk
Current Plan=p01
Default Exp/Contr=0,0
English Units
Geom File=g01
Flow File=f01
Plan File=p01
BEGIN DESCRIPTION:
END DESCRIPTION:
DSS Export Rating Curves= 0
DSS Export Rating Curve Sorted= 0
DSS Export Volume Flow Curves= 0
DXF OffsetX= 0
DXF OffsetY= 0
DXF ScaleX= 0
DXF ScaleY= 0

--- LttlCrk.p01 (plan) ---

Plan Title=Floodplain
Program Version=4.00
Geom File=g01
Flow File=f01
K Sum by GR=0
Std Step Tol=0.01
Critical Tol=0.01
Num of Std Step Trials=20
Max Error Tol=0.3
Flow Tol Ratio=0.001
Split Flow NTrial=30
Split Flow Tol=0.02
Split Flow Ratio=0.02
Log Output Level=0
Friction Slope Method=1
Unsteady Friction Slope Method=2
Unsteady Bridges Friction Slope Method=1
Global Log Level=0
CheckData=False
Run HTab=0
Run UNet=0
Run PostProcess=0
UNET Theta=0
UNET Theta Warmup=0
UNET ZTol=0
UNET ZSATol=0
UNET MxIter=0
UNET MaxInSteps=0
UNET DtIC=0
UNET DtMin=0
UNET MaxCRTS=0
UNET WFStab=0
UNET SFStab=0
UNET WFX=0
UNET SFX=0
UNET DSS MLevel=0
UNET DZMax Abort=0
UNET Convert EG Bridges=0
UNET Use Existing IB Tables=0
UNET Froude Limit=0
UNET Froude Power=0
Write IC File=0
Echo Input=False
Echo Output=False
Write Detailed=0

--- LttlCrk.f01 (steady flow) ---

Flow Title=NFF Regression Equation
Program Version=4.00
Number of Profiles= 1
Profile Names=P100yr
River Rch & RM=LttlCrk,Main            ,15996.2
 877.986
River Rch & RM=LttlCrk,Main            ,13296.8
954.5188
River Rch & RM=LttlCrk,Main            ,11468.4
1053.793
River Rch & RM=LttlCrk,Main            ,11044.9
1299.601
River Rch & RM=LttlCrk,Main            ,10396.2
1316.742
River Rch & RM=LttlCrk,Main            ,6811
1456.761
River Rch & RM=LttlCrk,Main            ,6443.7
1613.012
River Rch & RM=LttlCrk,Main            ,4500.5
1719.557
River Rch & RM=LttlCrk,Main            ,48.2
1893.703
Boundary for River Rch & Prof#=LttlCrk,Main            , 1
Up Type= 0
Dn Type= 3
Dn Slope=0.014534
DSS Import GetInterval= 0
DSS Import GetPeak= 0
DSS Import FillOption= 0

--- LttlCrk.g01 (geometry) ---

Geom Title=USGS 3m DEM
Program Version=4.00

River Reach=LttlCrk         ,Main
Reach XY= 30
     1810914.501      364962.192      1810447.09      365201.418
     1809935.515      365251.717     1809782.165      365448.005
     1809560.114      365321.645      1809093.93      365411.201
      1808906.23      365263.985     1808600.757      365297.109
     1808298.964      365575.592     1807944.419      365600.128
     1807791.069      365764.519     1807597.234      365712.994
     1807550.616       365833.22     1807173.989      366063.859
     1807106.515      366544.764     1807340.833      367179.019
      1807066.03      367718.811     1807146.999      368135.923
     1808025.388      369163.981       1808323.5      370176.091
     1807873.264      370994.367     1807634.038      370977.191
     1807368.309      370803.484     1806991.245      371070.653
     1806997.874       371354.83     1807146.048      371633.948
     1807608.276      371675.241     1807756.718      372140.198
     1807103.148      373232.404     1805832.868      374476.366

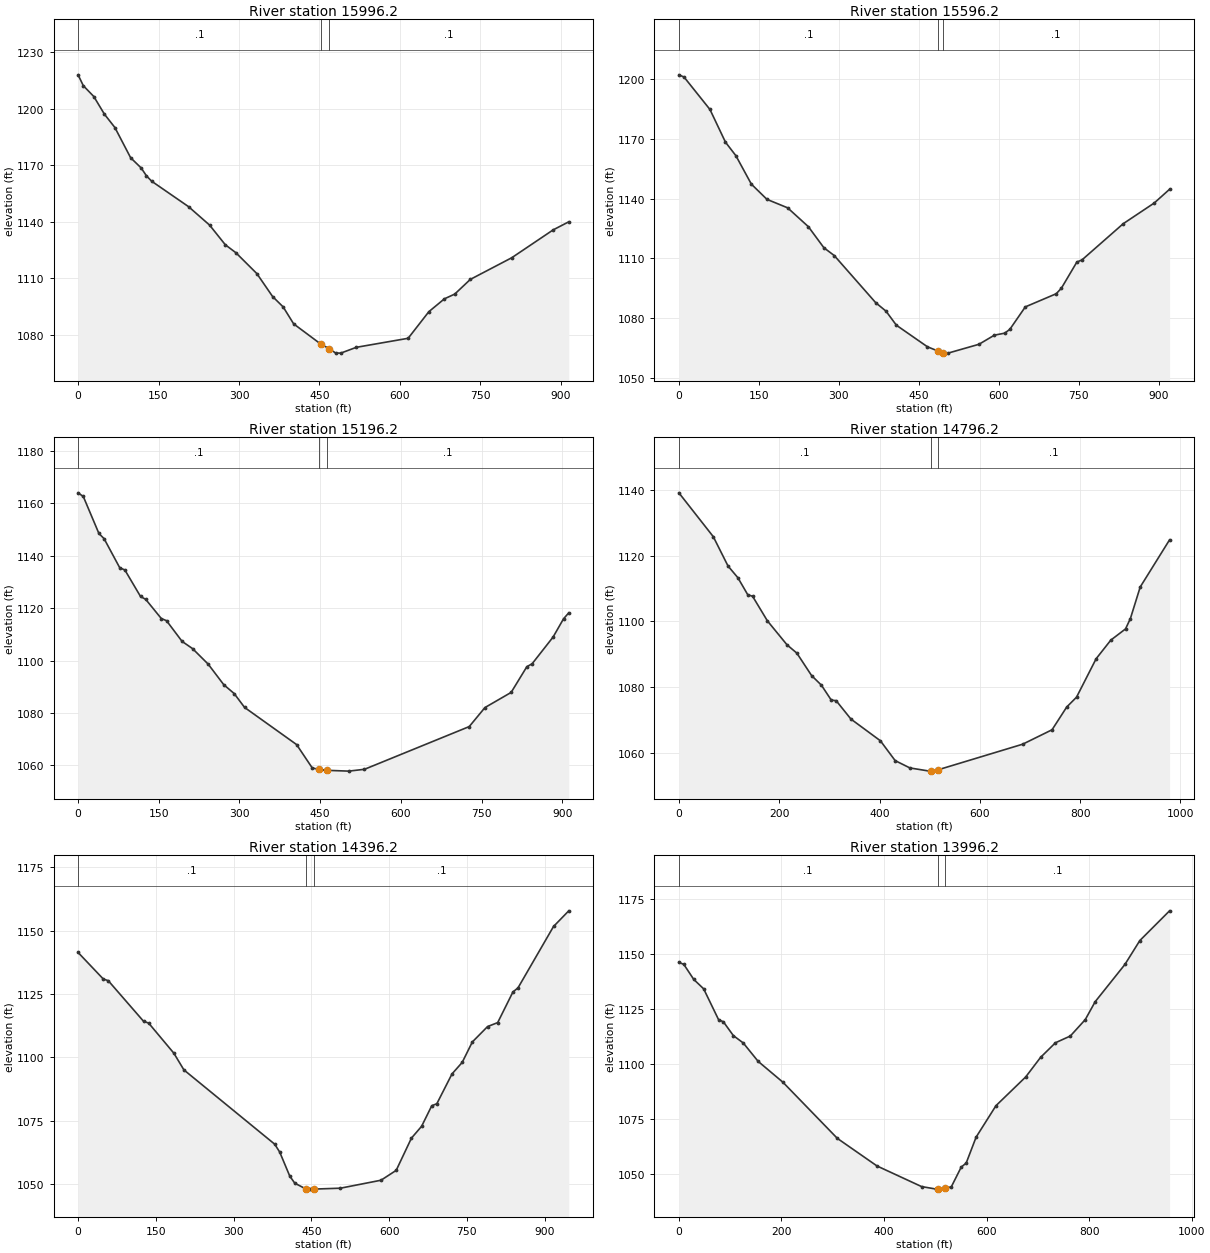
Type RM Length L Ch R = 1 ,15996.2 ,401.292,400,402.152
XS GIS Cut Line= 3
     1810690.789      364560.939     1810906.423      364968.087
     1811174.036      365334.815
#Sta/Elev= 30
       0  1217.9     9.8 1212.12    29.4 1206.37      49 1197.07    68.6 1189.96
      98 1173.92   117.6 1168.51   127.4 1164.36   137.2 1161.47   205.9 1147.99
   245.1 1138.22   274.5 1127.76   294.1 1123.57   333.3 1112.47   362.7 1100.29
   382.3 1094.81   401.9 1085.81   453.2 1074.94   468.2 1072.67     480 1070.37
   489.7  1070.3   518.7 1073.38   615.3 1078.17   653.9 1092.28   682.9  1099.1
   702.2 1101.62   731.2  1109.4   808.5  1120.9   885.7 1135.68   914.7 1139.94
#Mann= 3 , 0 , 0
       0      .1       0   453.2    .045       0   468.2      .1       0
Bank Sta=453.2,468.2
XS Rating Curve= 0 ,0
Exp/Cntr=0.3,0.1

Type RM Length L Ch R = 1 ,15596.2 ,389.644,400,408.154
XS GIS Cut Line= 3
     1810302.943      364730.994     1810550.372       365114.77
     1810798.469      365506.784
#Sta/Elev= 30
       0 1201.88     9.7 1200.76    58.3 1184.54    87.4 1168.19   106.9 1161.44
     136 1147.19   165.2 1139.59     204 1135.35   242.9 1125.92     272 1115.39
   291.5 1111.46   369.2  1087.9   388.6 1083.65     408 1076.63   466.3 1065.83
   485.6 1063.76   495.3 1062.73   504.9 1062.66   562.9 1067.08   591.9 1071.65
   611.3 1072.65   620.9 1074.58   649.9 1085.79   707.9 1092.37   717.6 1095.16
   746.6 1108.22   756.2 1109.29   833.6 1127.41   891.6 1137.73   920.5 1144.62
#Mann= 3 , 0 , 0
       0      .1       0   485.6    .045       0   495.3      .1       0
Bank Sta=485.6,495.3
XS Rating Curve= 0 ,0
Exp/Cntr=0.3,0.1

Type RM Length L Ch R = 1 ,15196.2 ,403.792,400,381.437
XS GIS Cut Line= 3
     1810126.843      364770.483     1810183.223       365221.52
     1810280.036      365668.724
#Sta/Elev= 30
       0 1164.07     9.7 1162.67    38.7 1148.56    48.4 1146.55    77.4 1135.47
      87  1134.6   116.1 1124.48   125.7 1123.39   154.7 1116.07   164.4 1115.24
   193.4 1107.32   212.8 1104.58   241.8 1098.66   270.8  1090.8   290.1 1087.43
   309.5 1082.12   406.2 1067.93   435.2 1059.03     447 1058.44     462  1058.1
   503.2 1057.79   532.4 1058.49   727.1  1074.8   756.3 1082.06     805 1087.85
   834.2 1097.67     844 1098.79   882.9 1108.97   902.4 1115.97   912.1 1118.24
#Mann= 3 , 0 , 0
       0      .1       0     447    .045       0     462      .1       0
Bank Sta=447,462
XS Rating Curve= 0 ,0
Exp/Cntr=0.3,0.1

Type RM Length L Ch R = 1 ,14796.2 ,382.91,400,422.406
XS GIS Cut Line= 3
     1809701.714       364874.62     1809865.847      365357.075
      1810180.61      365704.405
#Sta/Elev= 30
       0 1139.07    68.6 1125.73      98  1116.8   117.6 1113.25   137.2  1108.1
     147 1107.59   176.4 1100.14   215.6 1092.83   235.2 1090.31   264.6 1083.48
   284.2 1080.55   303.8 1076.02   313.6 1075.84     343 1070.25   401.8 1063.64
   431.2 1057.61   460.6 1055.38   499.8 1054.41   502.1 1054.47   517.1 1054.83
   685.4  1062.6     744 1066.99   773.3 1073.92   792.8  1076.9   831.9  1088.6
   861.2 1094.27   890.5 1097.67   900.2 1100.82   919.8 1110.43   978.3 1124.77
#Mann= 3 , 0 , 0
       0      .1       0   502.1    .045       0   517.1      .1       0
Bank Sta=502.1,517.1
XS Rating Curve= 0 ,0
Exp/Cntr=0.3,0.1

Type RM Length L Ch R = 1 ,14396.2 ,400.585,400,397.239
XS GIS Cut Line= 3
     1809613.189      364877.897     1809569.344      365323.065
     1809498.628      365817.289
#Sta/Elev= 30
       0 1141.38    48.6 1130.92    58.3 1130.24   126.4 1114.22   136.1 1113.54
   184.8 1101.65   204.2 1095.06   379.3 1065.78     389 1062.66   408.4 1053.18
   418.1 1050.39   439.8 1048.09   447.3 1048.05   454.8 1048.06   506.1 1048.42
   584.4 1051.56   613.7 1055.45   643.1 1068.16   662.7 1072.82   682.3 1080.93
   692.1 1081.73   721.4 1093.49     741 1098.02   760.6 1106.09     790 1112.16
   809.5 1113.72   838.9  1125.8   848.7 1127.42   917.2 1151.62   946.6  1157.8
#Mann= 3 , 0 , 0
       0      .1       0   439.8    .045       0   454.8      .1       0
Bank Sta=439.8,454.8
XS Rating Curve= 0 ,0
Exp/Cntr=0.3,0.1

Type RM Length L Ch R = 1 ,13996.2 ,377.786,374.24,364.821
XS GIS Cut Line= 3
     1809232.139      364897.126     1809193.846      365407.642
     1809183.962      365852.482
#Sta/Elev= 30
       0 1146.32     9.7 1145.33      29 1138.51    48.3 1134.22    77.3 1120.22
    86.9 1119.16   106.3 1112.89   125.6 1109.54   154.6 1101.16   202.8 1091.68
   309.1 1066.06   386.4  1053.5   473.3 1044.11   502.3 1042.95   504.5 1042.98
   519.5 1043.27   531.3 1044.01   550.6 1052.98   560.3 1054.83   579.7 1066.67
   618.4 1080.98   676.4 1094.08   705.4    1103   734.4 1109.65   763.4 1112.72
   792.5 1120.19   811.8 1128.34   869.8 1145.32   898.9 1156.21   956.9 1169.76
#Mann= 3 , 0 , 0
       0      .1       0   504.5    .045       0   519.5      .1       0
Bank Sta=504.5,519.5
XS Rating Curve= 0 ,0
Exp/Cntr=0.3,0.1

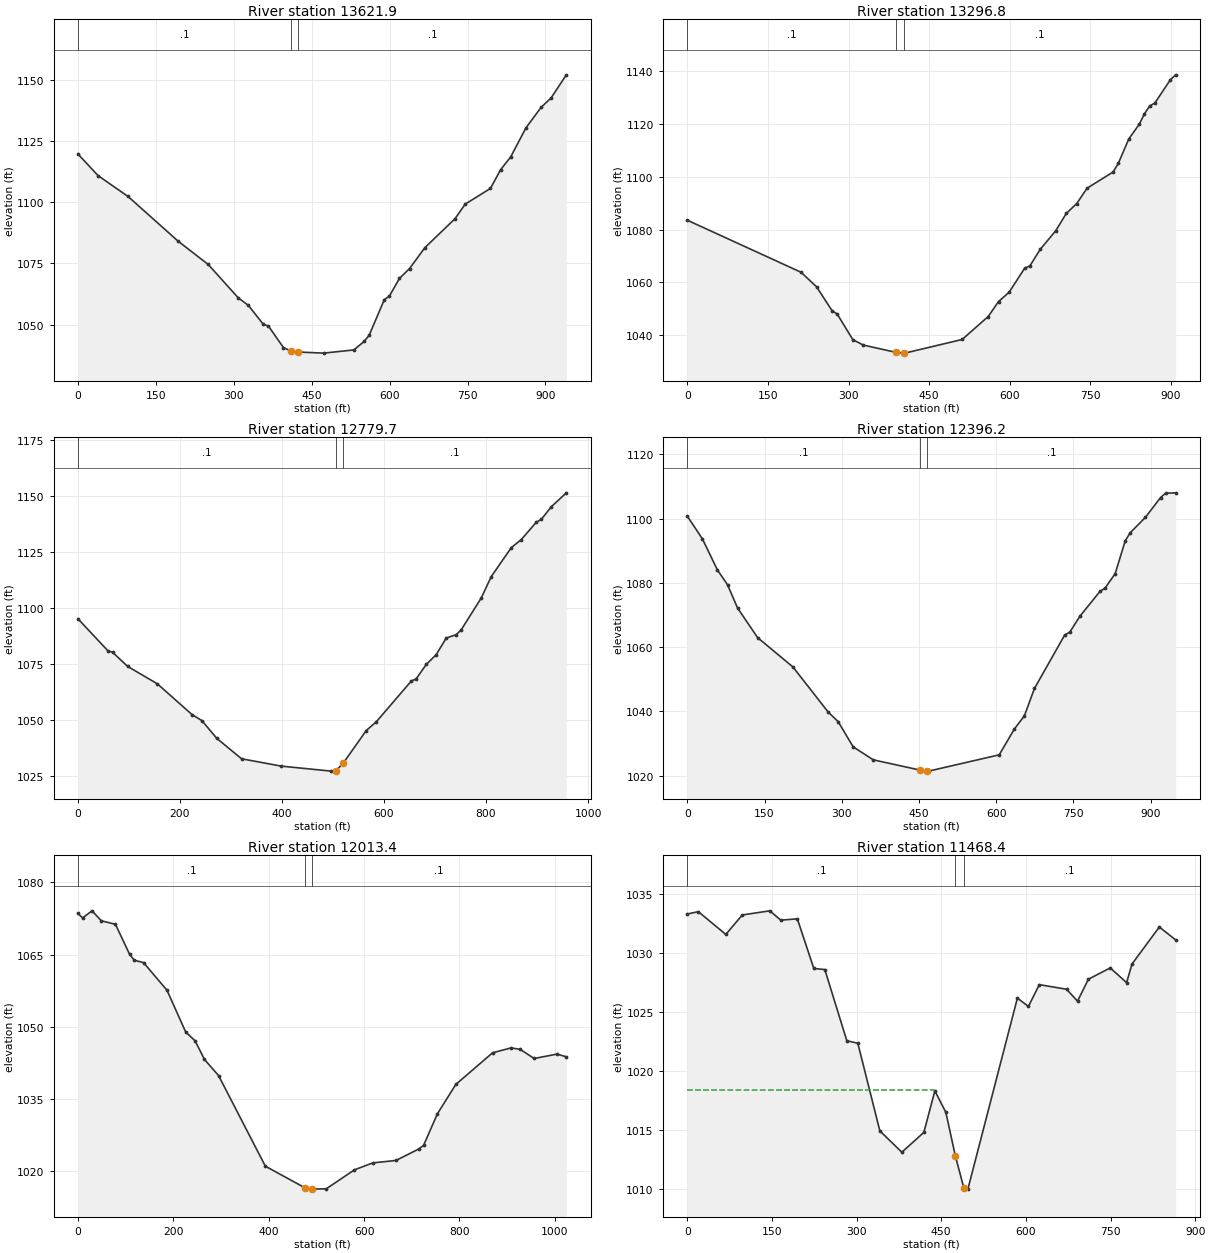
Type RM Length L Ch R = 1 ,13621.9 ,328.465,325.176,321.855
XS GIS Cut Line= 3
     1808917.408      364855.671      1808938.27      365298.988
     1808906.977       365794.46
#Sta/Elev= 30
       0 1119.74    38.6 1110.92    96.5 1102.36     193 1084.06   250.8 1074.55
   308.7 1060.89     328 1057.84     357 1050.04   366.6 1049.39   395.6 1040.58
   409.5  1039.2   424.5 1038.74     473 1038.29   531.4  1039.6   550.9 1043.08
   560.6 1045.57   589.8 1060.16   599.6 1061.62     619 1068.86   638.5  1072.9
   667.7 1081.38   726.1 1093.32   745.6 1099.24   794.2 1105.67   813.7 1113.31
   833.2 1118.58   862.4 1130.39   891.6 1138.79   911.1 1142.73   940.3 1152.13
#Mann= 3 , 0 , 0
       0      .1       0   409.5    .045       0   424.5      .1       0
Bank Sta=409.5,424.5
XS Rating Curve= 0 ,0
Exp/Cntr=0.3,0.1

Type RM Length L Ch R = 1 ,13296.8 ,520.541,517.02,513.091
XS GIS Cut Line= 3
     1808614.005      364903.355     1808609.921       365201.49
     1808723.527      365801.214
#Sta/Elev= 30
       0 1083.54   211.6 1063.79   240.5 1058.26   269.3  1049.2   278.9 1047.93
   307.9 1038.23   327.2 1036.17     388  1033.4     403 1033.13   404.7  1033.1
   511.3 1038.28   559.8 1046.99   579.1 1052.69   598.5 1056.16   627.6  1065.3
   637.3 1066.19   656.6 1072.49   685.7  1079.6   705.1 1086.12   724.5 1089.86
   743.8  1095.7   792.3 1101.85     802 1105.16   821.4  1114.4   840.7  1119.9
   850.4 1123.87   860.1 1126.87   869.8    1128   898.9 1136.89   908.6 1138.71
#Mann= 3 , 0 , 0
       0      .1       0     388    .045       0     403      .1       0
Bank Sta=388,403
XS Rating Curve= 0 ,0
Exp/Cntr=0.3,0.1

Type RM Length L Ch R = 1 ,12779.7 ,386.914,383.564,378.676
XS GIS Cut Line= 3
     1808039.598       365121.52     1808223.747      365507.608
     1808376.274      366014.763
#Sta/Elev= 30
       0  1095.2    58.3 1080.99    68.1 1080.18    97.2 1073.95   155.5 1066.15
   223.6 1052.39     243 1049.68   272.2 1041.75   320.8 1032.62   398.6 1029.35
   496.4 1027.11   505.1 1027.12   520.1  1030.7   565.1 1045.24   584.7 1049.12
   653.3 1067.33   663.1 1068.38   682.7 1074.78   702.4 1079.21     722  1086.6
   741.6  1088.1   751.4  1090.3   790.6 1104.51   810.2 1114.07   849.5 1126.99
   869.1 1130.62   898.5 1138.37   908.3 1139.63   927.9 1145.27   957.4  1151.5
#Mann= 3 , 0 , 0
       0      .1       0   505.1    .045       0   520.1      .1       0
Bank Sta=505.1,520.1
XS Rating Curve= 0 ,0
Exp/Cntr=0.3,0.1

Type RM Length L Ch R = 1 ,12396.2 ,390.789,382.745,376.237
XS GIS Cut Line= 3
     1807671.746      365242.331     1807889.405      365646.362
     1808141.753       366066.08
#Sta/Elev= 30
       0 1100.77    29.3 1093.71    58.6 1084.01    78.1 1079.43    97.6 1072.19
   136.7 1062.96   205.1 1053.86   273.4 1039.86   292.9 1036.86   322.2 1028.99
   361.3 1024.94   451.4 1021.78   466.4 1021.46   468.7 1021.43   605.9  1026.5
   635.2 1034.51   654.8 1038.64   674.4 1047.18   733.2 1063.81     743 1064.67
   762.6 1069.62   801.7 1077.38   811.5 1078.38   831.1 1082.87   850.7  1093.1
   860.5 1095.63   889.9  1100.4   919.3 1106.56   929.1 1107.92   948.7 1108.03
#Mann= 3 , 0 , 0
       0      .1       0   451.4    .045       0   466.4      .1       0
Bank Sta=451.4,466.4
XS Rating Curve= 0 ,0
Exp/Cntr=0.3,0.1

Type RM Length L Ch R = 1 ,12013.4 ,541.45,545.036,546.962
XS GIS Cut Line= 3
     1807249.936      365368.935     1807650.172      365801.843
     1807766.896       366220.46
#Sta/Elev= 30
       0 1073.55     9.8 1072.63    29.5  1074.1    49.1 1072.02    78.6  1071.3
   108.1  1065.1   117.9 1063.83   137.6 1063.32   186.7 1057.58     226 1048.87
   245.7 1047.05   265.3 1043.18   294.8 1039.83     393 1020.97   476.1 1016.47
   491.1  1016.2   520.8 1016.27   579.7 1020.21   618.5 1021.66   666.8 1022.16
   715.1 1024.57   724.8  1025.3   753.8 1031.87   792.4 1037.98   869.6 1044.57
   908.3 1045.58   927.6 1045.27   956.6 1043.38  1004.8 1044.29  1024.2 1043.73
#Mann= 3 , 0 , 0
       0      .1       0   476.1    .045       0   491.1      .1       0
Bank Sta=476.1,491.1
XS Rating Curve= 0 ,0
Exp/Cntr=0.3,0.1

Type RM Length L Ch R = 1 ,11468.4 ,451.214,423.475,395.496
XS GIS Cut Line= 3
     1806948.558      365634.736     1807266.272      366148.987
     1807356.121      366394.029
#Sta/Elev= 30
       0  1033.3    19.5  1033.5    68.2 1031.57    97.5 1033.22   146.2 1033.57
   165.7 1032.78     195 1032.89   224.2 1028.68   243.7 1028.59   282.7 1022.55
   302.2 1022.34   341.2 1014.91   380.2  1013.1   419.2 1014.78   438.7  1018.3
   458.2 1016.48   474.9 1012.81   489.9  1010.1   497.2 1009.97     585 1026.17
   604.5 1025.46   623.8 1027.31   672.1 1026.92   691.5 1025.91   710.8 1027.77
   749.5 1028.73   778.5 1027.48   788.1 1029.06   836.5  1032.2   865.5  1031.1
#Mann= 3 , 0 , 0
       0      .1       0   474.9    .045       0   489.9      .1       0
#XS Ineff= 2 , 0
          437.56 1018.36
Permanent Ineff=
       F       F
Bank Sta=474.9,489.9
XS Rating Curve= 0 ,0
Exp/Cntr=0.3,0.1

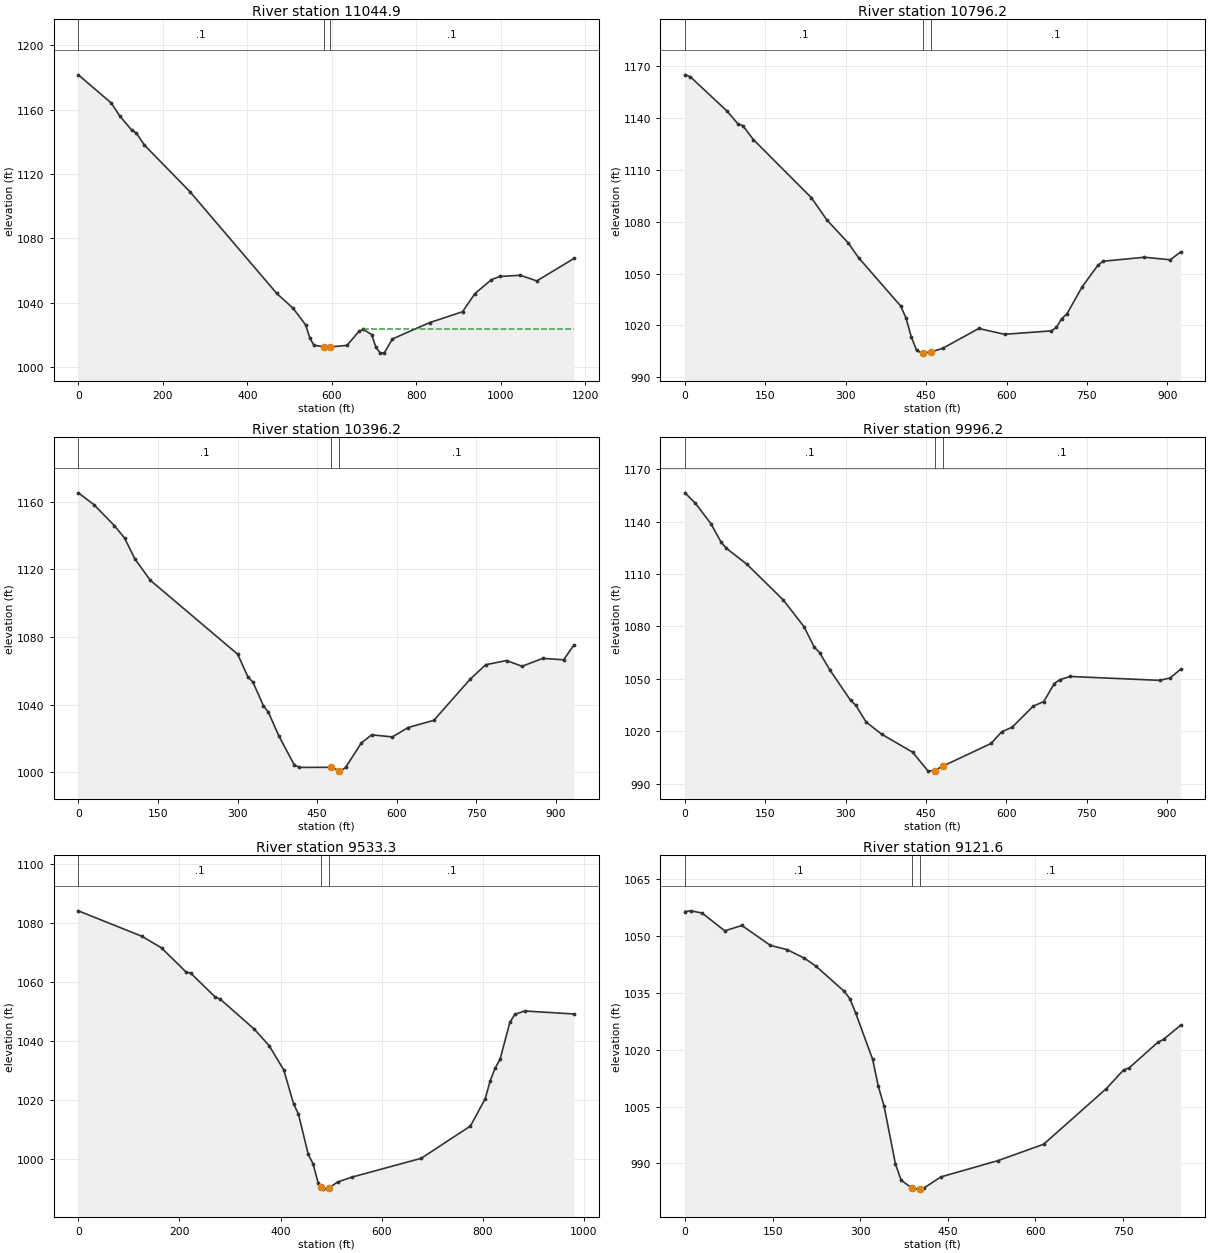
Type RM Length L Ch R = 1 ,11044.9 ,256.426,248.744,241.574
XS GIS Cut Line= 3
     1806518.893      366520.634     1807225.432      366418.534
     1807674.676      366512.466
#Sta/Elev= 30
       0 1181.64    78.2 1164.06    97.8 1156.11   127.1 1147.04   136.9 1145.58
   156.5 1137.94     264 1109.03   469.4 1045.79   508.5 1036.45   537.9 1026.22
   547.6 1018.23   557.4  1013.5   581.5 1012.65   596.5 1012.51   635.6 1013.46
     665 1022.41   674.8 1023.37   694.3  1020.1   704.1 1012.29   713.9 1008.89
   723.6 1008.64   743.2 1017.45   831.1 1027.58   909.2 1034.38   938.5 1045.66
   977.5 1054.31   997.1 1056.28  1045.9 1057.05    1085 1053.52  1172.8 1067.49
#Mann= 3 , 0 , 0
       0      .1       0   581.5    .045       0   596.5      .1       0
#XS Ineff= 2 , 0
                             676         1023.86
Permanent Ineff=
       F       F
Bank Sta=581.5,596.5
XS Rating Curve= 0 ,0
Exp/Cntr=0.3,0.1

Type RM Length L Ch R = 1 ,10796.2 ,393.063,400,394.119
XS GIS Cut Line= 3
     1806743.565      366830.164     1807154.937      366643.774
     1807621.421      366563.937
#Sta/Elev= 30
       0 1165.02     9.8 1163.93    78.5 1144.02    98.2 1136.81     108 1135.54
   127.6 1127.54   235.6 1093.97   265.1 1080.87   304.4  1067.8     324  1059.1
   402.5 1031.19   412.4 1024.31   422.2 1013.39     432 1005.65   441.8 1003.91
   444.1 1003.96   459.1 1004.63   480.6 1006.64   548.2 1018.17   596.5 1014.81
   683.4 1016.79   693.1 1018.78   702.7 1023.86   712.4 1026.46   741.4 1042.42
   770.4 1054.74     780 1057.11   857.3 1059.41   905.6 1057.96   924.9 1062.46
#Mann= 3 , 0 , 0
       0      .1       0   444.1    .045       0   459.1      .1       0
Bank Sta=444.1,459.1
XS Rating Curve= 0 ,0
Exp/Cntr=0.3,0.1

Type RM Length L Ch R = 1 ,10396.2 ,387.39,400,422.424
XS GIS Cut Line= 3
      1806818.02      367071.061     1807298.774      367012.584
     1807712.687      366836.451
#Sta/Elev= 30
       0 1165.26    29.1 1158.35    67.8 1145.95    87.2 1138.52   106.5 1126.26
   135.6  1113.6   300.3  1069.9   319.6  1056.5   329.3 1053.27   348.7 1039.52
   358.4 1035.52   377.8 1021.67   406.8  1004.6   416.5    1003   476.8 1003.06
   491.8 1001.07   494.1  1000.8   503.9 1003.03   533.2 1017.37   552.8 1022.27
   591.9 1021.01   621.2 1026.54   670.1 1030.83   738.5 1055.15   767.9 1063.69
     807 1066.15   836.3 1062.76   875.5 1067.45   914.6 1066.57   934.1  1075.4
#Mann= 3 , 0 , 0
       0      .1       0   476.8    .045       0   491.8      .1       0
Bank Sta=476.8,491.8
XS Rating Curve= 0 ,0
Exp/Cntr=0.3,0.1

Type RM Length L Ch R = 1 ,9996.2  ,477.197,462.843,445.176
XS GIS Cut Line= 3
     1806799.444      367178.179     1807229.416      367376.179
     1807608.701      367622.188
#Sta/Elev= 30
       0 1156.45    19.3 1150.52    48.3 1138.81    67.6 1128.09    77.3 1124.69
   115.9 1115.47   183.6 1095.07   222.2 1079.82   241.5 1068.04   251.2 1065.02
   270.5 1055.05   309.1 1037.67   318.8 1034.86   338.1 1025.24   367.1 1018.28
   425.1 1007.92     454  997.11   465.9  997.46   480.9  999.88   571.6 1012.97
   591.3 1019.61     611  1022.3   650.3 1034.33   669.9 1036.94   689.6 1047.24
   699.4 1049.39   719.1 1051.31   886.1 1049.09   905.8 1050.44   925.5 1055.43
#Mann= 3 , 0 , 0
       0      .1       0   465.9    .045       0   480.9      .1       0
Bank Sta=465.9,480.9
XS Rating Curve= 0 ,0
Exp/Cntr=0.3,0.1

Type RM Length L Ch R = 1 ,9533.3  ,414.848,411.692,408.536
XS GIS Cut Line= 3
     1806604.335       367887.83     1807163.697      367774.393
     1807570.819      367731.469
#Sta/Elev= 30
       0 1084.03   125.8 1075.39   164.5 1071.46   212.8 1063.32   222.5 1062.85
   270.9 1054.75   280.5 1054.09   348.3 1043.84   377.3 1038.32   406.3 1030.05
   425.6 1018.62   435.3  1015.1   454.7 1001.42   464.3  998.18     474  991.88
   480.8  990.31   483.7  989.64   495.8  990.02   512.7  992.06   541.7  993.74
     678 1000.09   775.4 1011.04   804.7 1020.33   814.4 1026.34   824.2 1030.66
   833.9 1033.64   853.4 1046.22   863.2 1048.93   882.7 1050.06   980.1 1049.04
#Mann= 3 , 0 , 0
       0      .1       0   480.8    .045       0   495.8      .1       0
Bank Sta=480.8,495.8
XS Rating Curve= 0 ,0
Exp/Cntr=0.3,0.1

Type RM Length L Ch R = 1 ,9121.6  ,304.062,296.346,288.629
XS GIS Cut Line= 3
     1806796.005      368302.462      1807218.46       368153.82
     1807606.676       368054.86
#Sta/Elev= 30
       0 1056.52     9.7 1056.71    29.2 1056.13    68.1 1051.43    97.4 1052.84
     146  1047.6   175.2 1046.44   204.4  1044.2   223.9 1042.13   272.6 1035.45
   282.3 1033.47   292.1 1029.76   321.3 1017.45     331 1010.32   340.7 1005.22
   360.2   989.9     370  985.56   387.8  983.56   399.2  983.21   402.8  983.32
   408.9  983.49   438.1  986.44   535.8  990.74     614  995.07   721.4 1009.77
   750.8 1014.68   760.5 1015.25   809.4 1021.98   819.2 1022.76   848.5  1026.5
#Mann= 3 , 0 , 0
       0      .1       0   387.8    .045       0   402.8      .1       0
Bank Sta=387.8,402.8
XS Rating Curve= 0 ,0
Exp/Cntr=0.3,0.1

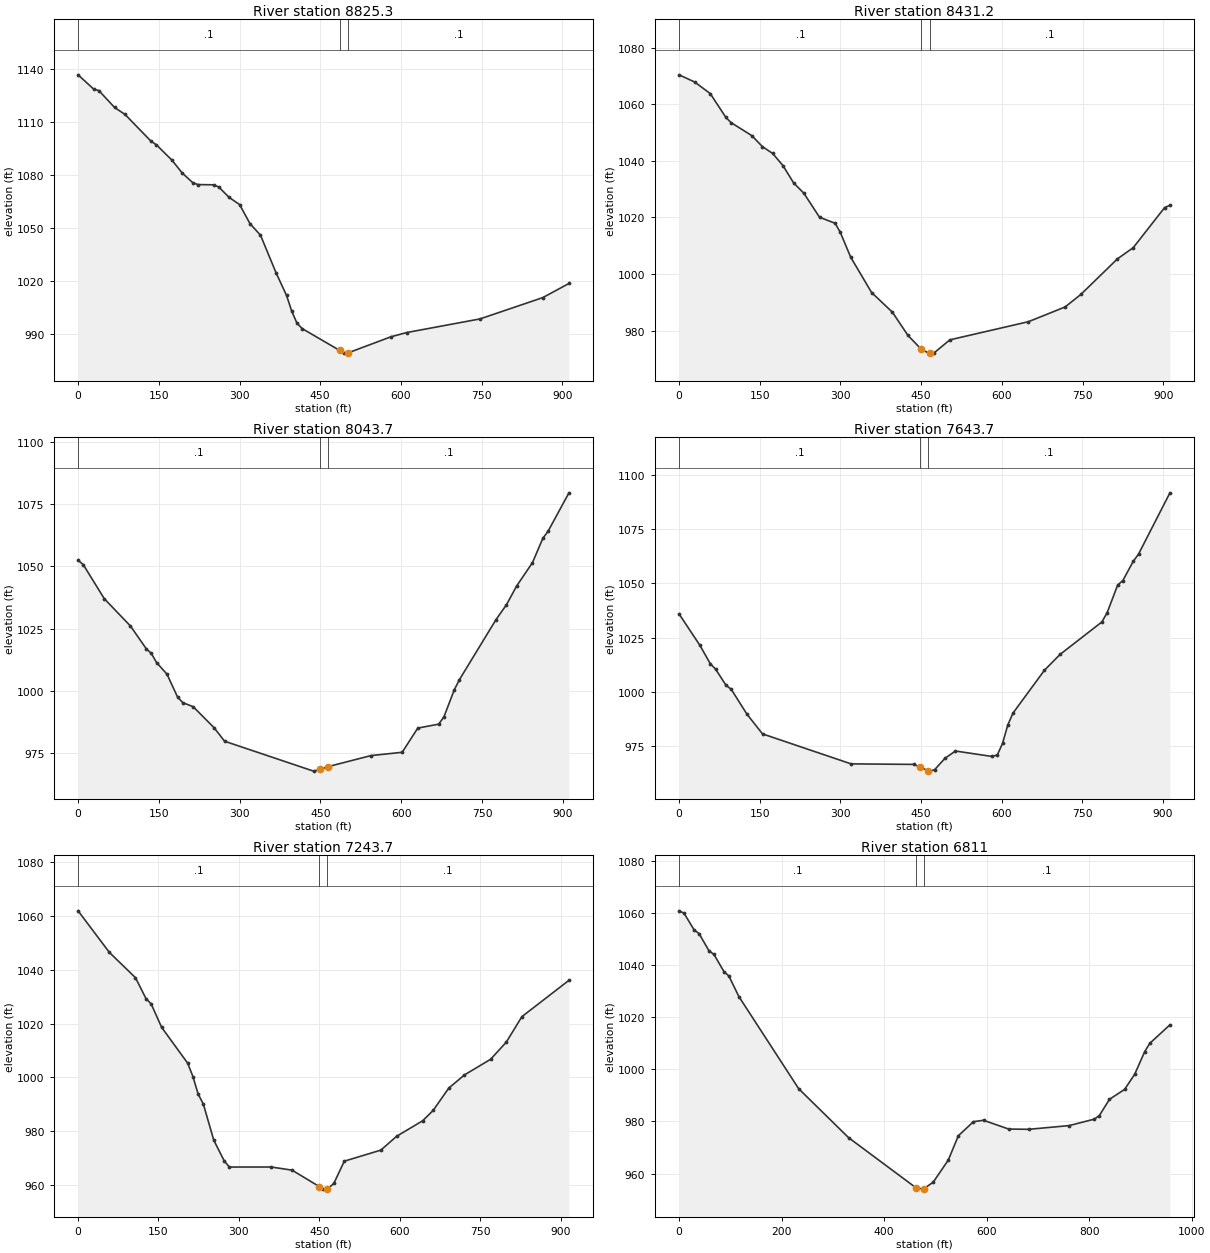
Type RM Length L Ch R = 1 ,8825.3  ,402.16,394.073,385.219
XS GIS Cut Line= 3
     1806978.731      368771.066     1807293.453      368442.225
     1807650.204      368156.569
#Sta/Elev= 30
       0  1136.5    29.1  1128.4    38.7 1127.58    67.8 1118.04    87.2 1114.12
   135.6 1098.95   145.3    1097   174.3 1088.31   193.7 1080.94   213.1 1075.54
   222.7 1074.45   251.8 1074.32   261.5 1073.07   280.9 1067.15   300.2 1063.14
   319.6  1052.3     339 1045.85     368 1024.52   387.4 1011.78   397.1 1002.85
   406.8  996.07   416.4  993.05   485.9  980.73   494.1  979.16   500.9  979.21
   581.6  988.42   610.8   990.8   746.9   998.5   863.6 1010.55   912.2 1018.54
#Mann= 3 , 0 , 0
       0      .1       0   485.9    .045       0   500.9      .1       0
Bank Sta=485.9,500.9
XS Rating Curve= 0 ,0
Exp/Cntr=0.3,0.1

Type RM Length L Ch R = 1 ,8431.2  ,378.854,387.513,395.443
XS GIS Cut Line= 3
     1807341.595      369104.893     1807578.102      368716.682
     1807801.474      368316.969
#Sta/Elev= 30
       0 1070.37      29 1067.83      58 1063.74      87 1055.32    96.7 1053.48
   135.4 1048.88   154.8 1045.03   174.1 1042.59   193.4 1038.24   212.8 1032.23
   232.1 1028.52   261.1 1020.07   290.2 1017.93   299.8 1014.68   319.2  1005.9
   357.9  993.48   396.5  986.55   425.6   978.3   450.6  973.37   464.3  972.07
   465.6  972.08   474.1  972.16   503.3  976.76   649.4  983.17   717.6  988.37
   746.9   992.8     815 1005.38   844.3 1009.32   902.7  1023.5   912.5 1024.27
#Mann= 3 , 0 , 0
       0      .1       0   450.6    .045       0   465.6      .1       0
Bank Sta=450.6,465.6
XS Rating Curve= 0 ,0
Exp/Cntr=0.3,0.1

Type RM Length L Ch R = 1 ,8043.7  ,395.135,400,407.669
XS GIS Cut Line= 3
     1807481.768      369266.569     1807844.912       368989.89
     1808187.585      368690.941
#Sta/Elev= 30
       0 1052.48     9.7 1050.66    48.6 1037.04    97.1  1026.1   126.3 1017.03
     136 1015.06   145.7 1011.41   165.1 1006.73   184.6  997.61   194.3  995.33
   213.7  993.69   252.6  985.23     272  979.84   437.1  967.84     449  968.51
     464  969.64   543.6  974.07   601.7   975.4   630.7  985.11   669.4  986.69
   679.1  989.54   698.4 1000.45   708.1 1004.59   775.8  1028.6   795.2 1034.56
   814.5 1042.22   843.6  1051.5   862.9 1061.27   872.6  1064.1   911.3 1079.51
#Mann= 3 , 0 , 0
       0      .1       0     449    .045       0     464      .1       0
Bank Sta=449,464
XS Rating Curve= 0 ,0
Exp/Cntr=0.3,0.1

Type RM Length L Ch R = 1 ,7643.7  ,400.314,400,399.13
XS GIS Cut Line= 3
     1807646.808      369489.257     1808061.314      369299.635
     1808487.457      369133.503
#Sta/Elev= 30
       0 1035.93    38.8 1021.45    58.2 1012.95    67.9 1010.53    87.3 1003.08
      97 1001.23   126.1  989.83   155.2  980.69     320  966.88   436.4  966.64
   448.3  965.48   463.3   963.7   465.6  963.54   475.3  964.17   494.7  969.46
   514.2   972.8   582.3  970.29   592.1  971.03   601.8  976.31   611.5  984.76
   621.3  990.29   679.6 1009.95   708.8 1017.29   786.7 1032.26   796.4 1036.51
   815.9  1049.2   825.6 1051.32   845.1 1060.21   854.8  1063.5   913.2  1091.7
#Mann= 3 , 0 , 0
       0      .1       0   448.3    .045       0   463.3      .1       0
Bank Sta=448.3,463.3
XS Rating Curve= 0 ,0
Exp/Cntr=0.3,0.1

Type RM Length L Ch R = 1 ,7243.7  ,424.771,432.734,439.944
XS GIS Cut Line= 3
     1807771.192      369869.808     1808185.671      369675.908
     1808606.764       369495.45
#Sta/Elev= 30
       0 1061.98    58.4 1046.49   107.1 1037.07   126.6 1029.32   136.3 1027.33
   155.8  1018.6   204.5 1005.22   214.2 1000.27   223.9  993.78   233.7  989.98
   253.1  976.57   272.6  968.84   282.3  966.55   360.2  966.56   399.2  965.39
   450.1  959.26   457.6  958.32   465.1  958.36   477.1  960.43   496.6  968.73
   564.8  972.85   594.1  977.98   642.8  983.78   662.3  987.62   691.5  995.94
   720.8 1000.86   769.5 1006.67   798.8 1013.06     828 1022.58   915.7 1036.09
#Mann= 3 , 0 , 0
       0      .1       0   450.1    .045       0   465.1      .1       0
Bank Sta=450.1,465.1
XS Rating Curve= 0 ,0
Exp/Cntr=0.3,0.1

Type RM Length L Ch R = 1 ,6811    ,354.788,367.266,382.807
XS GIS Cut Line= 3
     1807825.904      370133.006     1808348.919      370086.162
     1808743.993      370262.185
#Sta/Elev= 30
       0 1060.74     9.7 1059.82    29.2 1053.46    38.9 1052.03    58.3 1045.44
    68.1    1044    87.5 1037.46    97.2 1035.74   116.7 1027.85   233.4  992.52
   330.6  973.78   462.3  954.53   476.5  954.03   477.3  954.14   495.9  956.73
   525.1  965.14   544.8  974.49   574.3  979.89   593.9  980.43   643.1  977.06
   682.4  976.97     761  978.39   810.2  980.87     820  982.26   839.7  988.48
   869.2  992.27   888.8  998.05   908.5  1006.8   918.3 1009.93   957.6 1017.03
#Mann= 3 , 0 , 0
       0      .1       0   462.3    .045       0   477.3      .1       0
Bank Sta=462.3,477.3
XS Rating Curve= 0 ,0
Exp/Cntr=0.3,0.1

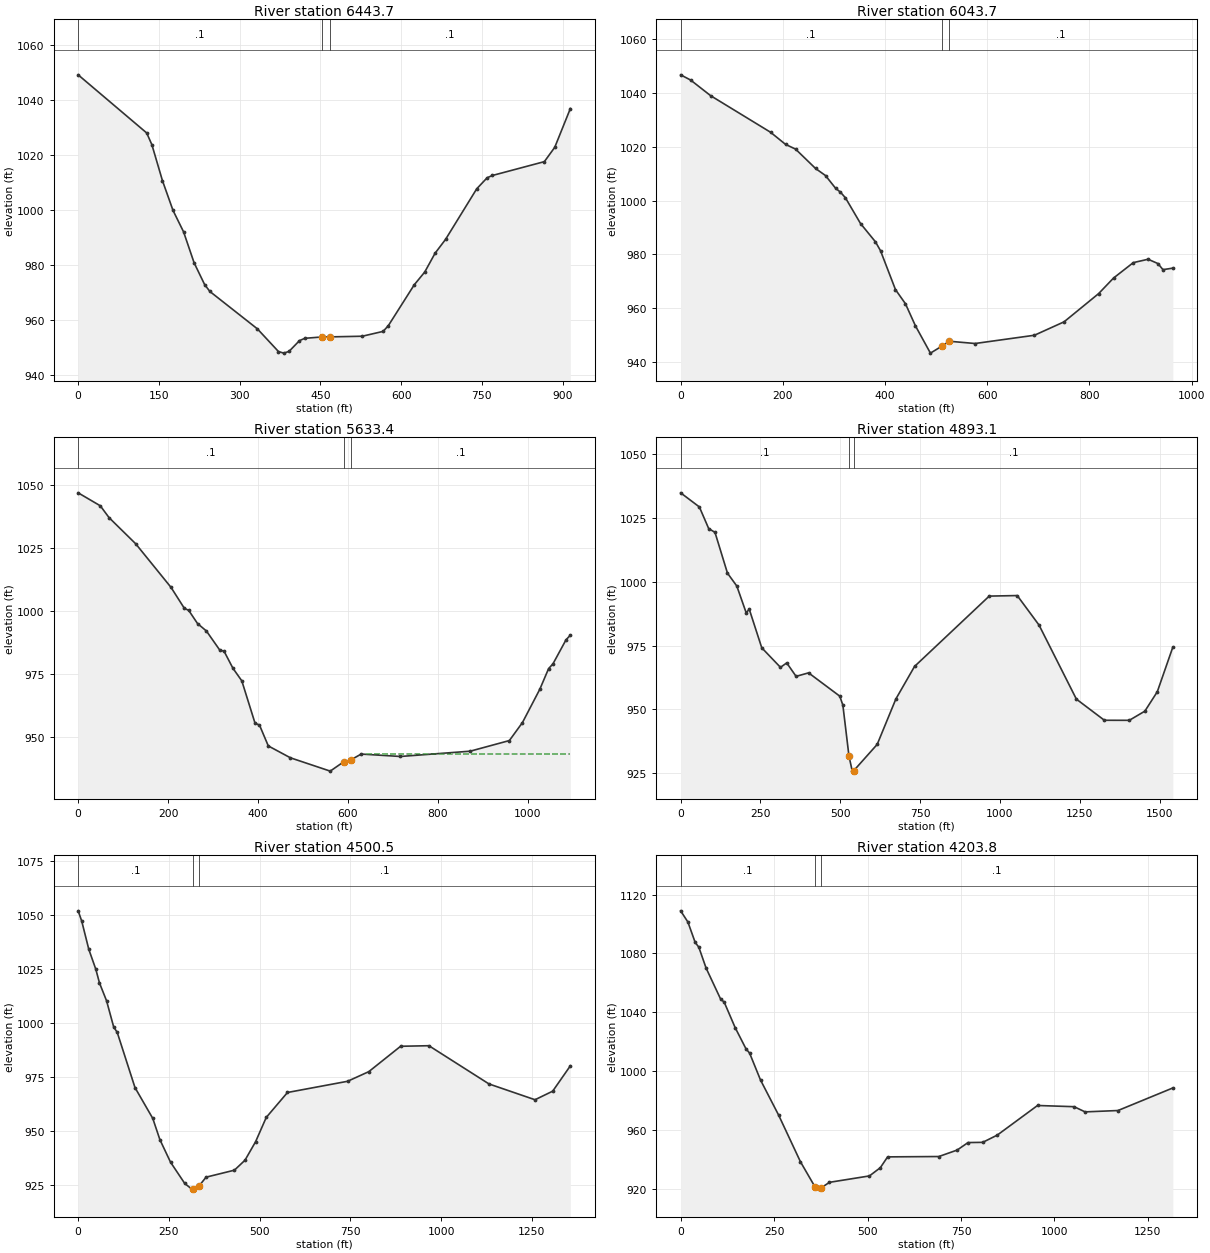
Type RM Length L Ch R = 1 ,6443.7  ,387.998,400,404.093
XS GIS Cut Line= 3
     1807810.254       370246.59     1808230.507      370433.875
      1808616.56      370672.979
#Sta/Elev= 30
       0 1049.13   127.3 1027.98     137 1023.67   156.6  1010.6   176.2  999.79
   195.8  991.99   215.4  980.72   234.9  972.81   244.7  970.29   332.8  956.71
     372  948.45   381.8  947.86   391.6  948.48   411.1  952.41   420.9  953.25
   452.6  953.74   467.6  953.77   527.7  954.01   566.4  955.77     576  957.82
   624.3  972.74   643.7  977.36     663  984.24   682.3  989.22   740.3 1007.66
   759.6 1011.67   769.3  1012.5   865.9 1017.54   885.2 1022.75   914.2 1036.87
#Mann= 3 , 0 , 0
       0      .1       0   452.6    .045       0   467.6      .1       0
Bank Sta=452.6,467.6
XS Rating Curve= 0 ,0
Exp/Cntr=0.3,0.1

Type RM Length L Ch R = 1 ,6043.7  ,404.896,410.297,425.136
XS GIS Cut Line= 3
     1807736.012      370360.563     1808040.317      370779.946
     1808372.235      371076.349
#Sta/Elev= 30
       0 1046.81    19.6 1044.86    58.7 1039.05     176 1025.44   205.3 1020.93
   224.9 1019.17     264 1011.97   283.5 1009.33   303.1 1004.63   312.8 1003.14
   322.6 1001.02     352  991.49   381.3  984.66   391.1  981.38   420.4   966.9
   439.9  961.65   459.5  953.41   488.8  943.27   510.7  945.81   525.7  947.69
   576.2  946.85   692.3  949.92   750.3  954.91     818  965.42   847.1   971.2
   885.8  976.94   914.8   978.2   934.1  976.58   943.8  974.33   963.2  974.89
#Mann= 3 , 0 , 0
       0      .1       0   510.7    .045       0   525.7      .1       0
Bank Sta=510.7,525.7
XS Rating Curve= 0 ,0
Exp/Cntr=0.3,0.1

Type RM Length L Ch R = 1 ,5633.4  ,749.368,740.345,726.729
XS GIS Cut Line= 3
     1807655.311      370421.647     1807758.264      371052.332
     1808105.591      371346.535
#Sta/Elev= 30
       0 1046.82    49.2 1041.67    68.8 1036.95   127.8 1026.61   206.5 1009.26
     236 1000.97   245.8 1000.13   265.4   994.9   285.1  991.95   314.6  984.42
   324.4   983.9   344.1  977.14   363.8  972.15   393.3  955.28   403.1  954.59
   422.7   946.3   471.9  941.58   560.4  936.29   590.5  940.02   605.5  940.69
   629.2  943.07   716.5  942.11   871.5  944.21   958.6  948.43   987.7  955.58
  1026.4  968.85  1045.8     977  1055.5  978.89  1084.5  988.43  1094.2  990.29
#Mann= 3 , 0 , 0
       0      .1       0   590.5    .045       0   605.5      .1       0
#XS Ineff= 2 , 0
                          639.06          943.27
Permanent Ineff=
       F       F
Bank Sta=590.5,605.5
XS Rating Curve= 0 ,0
Exp/Cntr=0.3,0.1

Type RM Length L Ch R = 1 ,4893.1  ,419.426,392.565,365.704
XS GIS Cut Line= 3
     1806737.331      370547.733     1807163.697      370978.012
     1808007.445      371382.229
#Sta/Elev= 30
       0 1034.86    58.6 1029.33    87.9 1020.83   107.5 1019.38   146.6 1003.39
   175.9  998.33   205.2  987.86   214.9  989.24     254  974.13   312.6  966.47
   332.2  968.21   361.5  962.94   400.6  964.31   498.3  955.18     508  951.65
   527.1   931.7   537.4   925.8   542.1  925.98   615.5  936.28     674  954.09
   732.4  966.82   966.3  994.39    1054   994.6  1122.3  983.03  1239.2  954.02
  1326.9  945.73  1404.9  945.71  1453.6   949.3  1492.6  956.91  1541.3  974.41
#Mann= 3 , 0 , 0
       0      .1       0   527.1    .045       0   542.1      .1       0
Bank Sta=527.1,542.1
XS Rating Curve= 0 ,0
Exp/Cntr=0.3,0.1

Type RM Length L Ch R = 1 ,4500.5  ,299.472,296.752,294.032
XS GIS Cut Line= 3
     1806681.799      371395.113     1807034.505      371248.935
     1807988.363      371447.613
#Sta/Elev= 30
       0 1052.12     9.8 1047.39    29.4 1034.24    48.9 1024.94    58.7 1018.73
    78.3 1010.43    97.9  998.31   107.7  995.79   156.6  970.23   205.6  955.95
   225.2  946.11   254.5  935.68   293.7  925.81   313.3  923.19   317.7  923.42
   332.7  924.57   352.4  928.73   430.5  931.97   459.7  936.59     489   945.2
   518.2   956.4   576.7  967.96   742.3  973.15   800.8  977.62   888.4  989.37
   966.4  989.63    1132  971.91  1258.7   964.6  1307.4  968.57  1356.1  980.32
#Mann= 3 , 0 , 0
       0      .1       0   317.7    .045       0   332.7      .1       0
Bank Sta=317.7,332.7
XS Rating Curve= 0 ,0
Exp/Cntr=0.3,0.1

Type RM Length L Ch R = 1 ,4203.8  ,558.046,553.661,567.157
XS GIS Cut Line= 3
      1806769.41      371725.004     1807243.396       371458.18
     1808012.863      371530.434
#Sta/Elev= 30
       0 1108.93    19.4 1101.32    38.9 1087.43    48.6 1084.23      68 1070.05
   106.8    1049   116.6  1046.8   145.7 1029.58   174.8 1015.09   184.5 1012.16
   213.7  993.86   262.3  969.92   320.5  938.29   359.9  920.99   369.1  919.67
   374.9  920.37   398.2   924.3   505.1  928.65   534.2  934.24   553.7   941.6
   690.7  941.84   739.6  946.22   768.9  951.34   808.1  951.48   847.2  956.43
   954.8  976.55  1052.6  975.73    1082   972.2    1170  973.12  1316.8  988.48
#Mann= 3 , 0 , 0
       0      .1       0   359.9    .045       0   374.9      .1       0
Bank Sta=359.9,374.9
XS Rating Curve= 0 ,0
Exp/Cntr=0.3,0.1