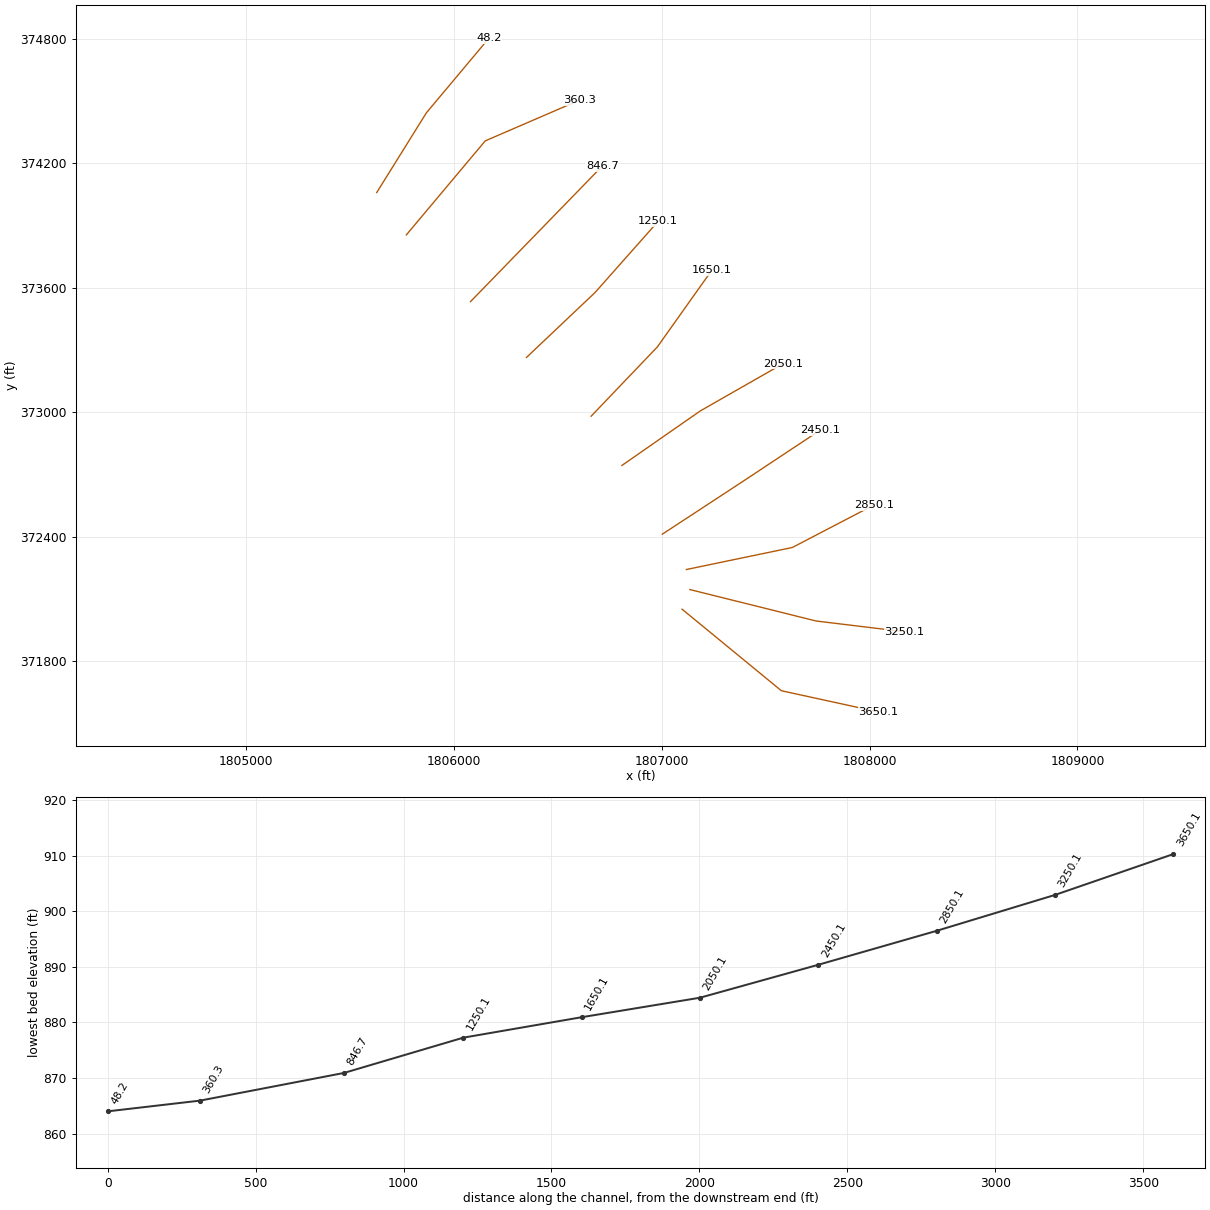
HEC-RAS study LttlCrk.prj: LttlCrk

--- LttlCrk.g01 (geometry) --- (continued)

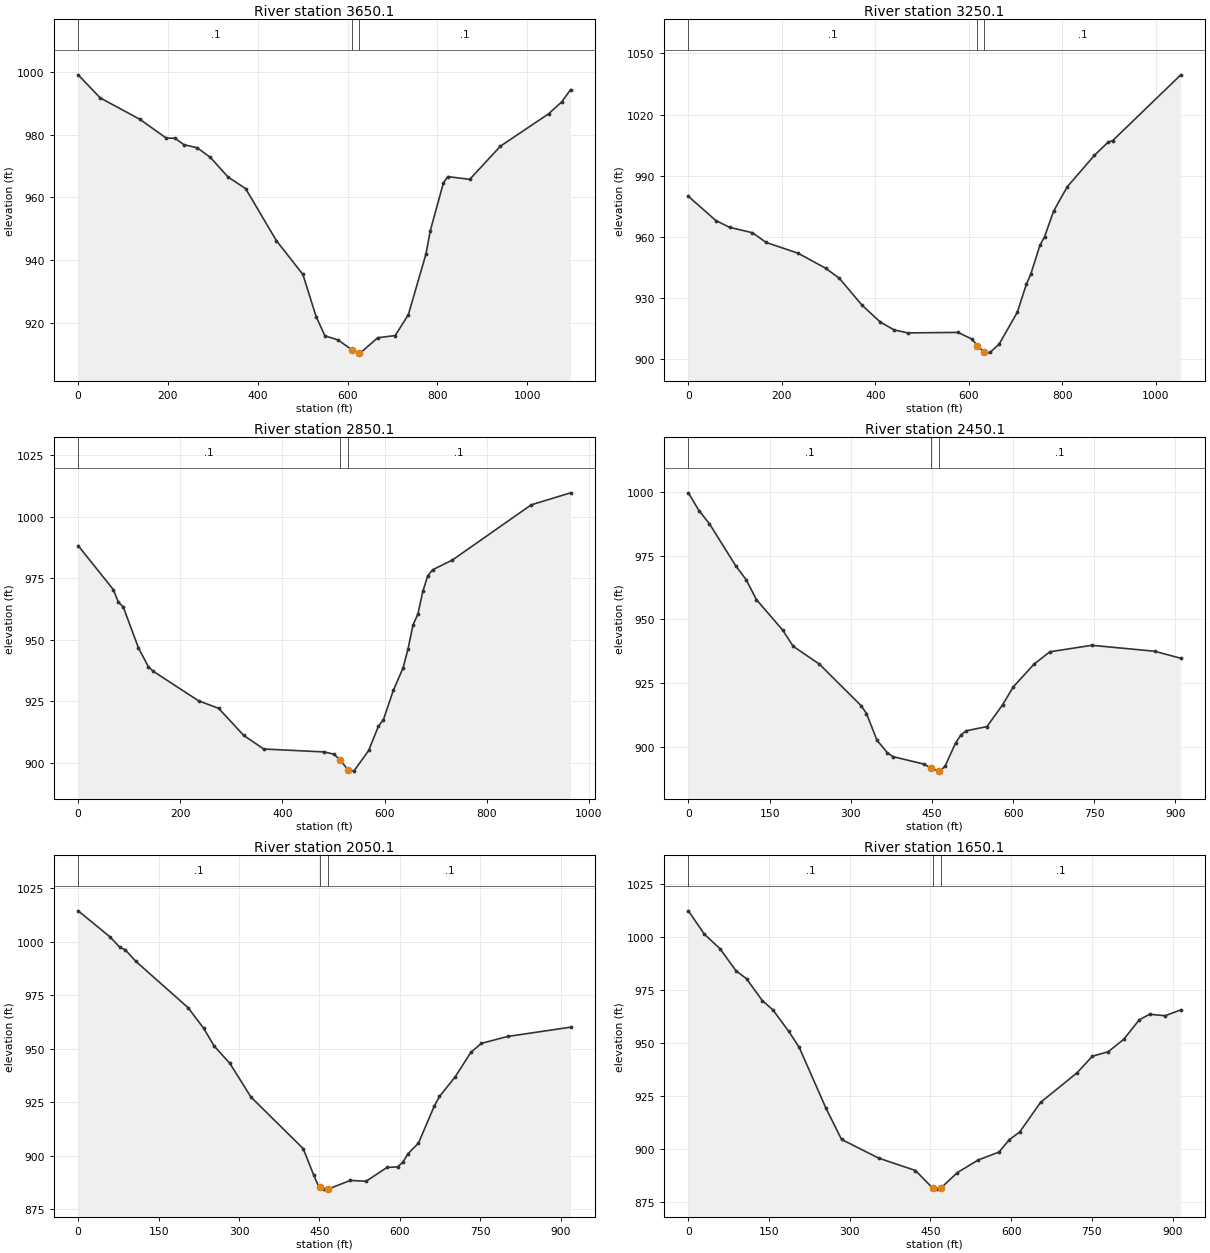
Type RM Length L Ch R = 1 ,3650.1  ,390.114,400,394.882
XS GIS Cut Line= 3
     1807098.401      372051.909     1807575.972      371659.089
     1808043.266      371557.019
#Sta/Elev= 30
       0  999.15    49.1  991.78   137.4  984.96   196.3  978.94   215.9  978.92
   235.6  976.84     265  975.88   294.5  972.79   333.7  966.54     373  962.82
   441.7  946.18   500.6  935.41     530  921.98   549.7  915.82   579.1  914.51
   610.9  911.22   625.9  910.31   628.1   910.3   667.2  915.21   706.2  915.91
   735.5  922.61   774.6   941.9   784.3  949.39   813.6  964.71   823.4  966.66
   872.2  965.78   940.5  976.37  1047.9  986.71  1077.2  990.53  1096.7  994.42
#Mann= 3 , 0 , 0
       0      .1       0   610.9    .045       0   625.9      .1       0
Bank Sta=610.9,625.9
XS Rating Curve= 0 ,0
Exp/Cntr=0.3,0.1

Type RM Length L Ch R = 1 ,3250.1  ,388.518,400,414.693
XS GIS Cut Line= 3
     1807135.938      372146.571     1807743.224      371995.119
     1808167.672      371943.551
#Sta/Elev= 30
       0  979.86    58.7  968.01      88  964.68   136.9  962.03   166.3  957.26
   234.7  951.96   293.4  944.63   322.7  939.71   371.6  926.44   410.7  918.17
   440.1  914.34   469.4  912.88     577  913.11   606.3  909.87   618.4  906.67
   633.4  903.26   635.6  902.95   645.3  903.26   664.8  907.39   703.6  922.95
   723.1  936.77   732.8  941.87   752.2  955.95   761.9  959.97   781.4  972.63
   810.5  984.55   868.8 1000.01     898 1006.48   907.7  1007.2  1053.5 1039.49
#Mann= 3 , 0 , 0
       0      .1       0   618.4    .045       0   633.4      .1       0
Bank Sta=618.4,633.4
XS Rating Curve= 0 ,0
Exp/Cntr=0.3,0.1

Type RM Length L Ch R = 1 ,2850.1  ,391.378,400,402.371
XS GIS Cut Line= 3
     1807119.126      372243.281     1807628.672      372349.328
     1808021.826      372554.451
#Sta/Elev= 30
       0  988.27    68.7   970.4    78.6  965.33    88.4  963.25   117.8  946.78
   137.5  938.95   147.3  937.08   235.7  925.11     275  922.05   324.1  911.04
   363.3  905.49   481.2  904.31   500.8  903.38     513  900.91     528  897.14
   539.7  896.49   568.7  904.89   587.9  914.81   597.6  917.44   616.9  929.31
   636.1  938.51   645.8  946.25   655.4   955.9   665.1  960.45   674.7  969.64
   684.3  975.97     694  978.45   732.5  982.38   886.8 1004.85   963.9 1009.75
#Mann= 3 , 0 , 0
       0      .1       0     513    .045       0     528      .1       0
Bank Sta=513,528
XS Rating Curve= 0 ,0
Exp/Cntr=0.3,0.1

Type RM Length L Ch R = 1 ,2450.1  ,402.961,400,398.443
XS GIS Cut Line= 3
     1807003.421      372413.628      1807383.83       372663.24
     1807763.009      372914.824
#Sta/Elev= 30
       0  999.71    19.4  992.75    38.7  987.61    87.1  971.16   106.5  965.64
   125.8  957.73   174.3  945.77   193.6  939.43     242  932.42   319.5  916.03
   329.1  913.01   348.5  902.52   367.9  897.57   377.5  896.11   435.6  893.12
   447.5  891.65   462.5  890.42   464.7  890.38   474.4  892.33   493.7  901.43
   503.4   904.5   513.1  906.21   551.8  907.89   580.9   916.5   600.2  923.42
   638.9  932.44     668  937.26   745.4  939.81   861.6  937.48     910  934.71
#Mann= 3 , 0 , 0
       0      .1       0   447.5    .045       0   462.5      .1       0
Bank Sta=447.5,462.5
XS Rating Curve= 0 ,0
Exp/Cntr=0.3,0.1

Type RM Length L Ch R = 1 ,2050.1  ,395.411,400,410.042
XS GIS Cut Line= 3
      1806808.66      372744.557     1807184.955      373006.874
     1807583.925      373235.109
#Sta/Elev= 30
       0 1014.45    58.6 1002.44    78.1  997.34    87.8  996.28   107.4   990.9
     205  969.21   234.2  959.54   253.8  951.26     283  943.17   322.1  927.52
   419.7  903.37   439.2  891.09   448.9  885.52   451.2  885.27   458.7  884.45
   466.2  884.46   507.6  888.53   536.9  888.12   576.1  894.59   595.6  894.82
   605.4  896.97   615.2  900.97   634.7  905.96   664.1  923.21   673.9  927.72
   703.2  936.92   732.5  948.37   752.1  952.54     801  955.77   918.3  960.09
#Mann= 3 , 0 , 0
       0      .1       0   451.2    .045       0   466.2      .1       0
Bank Sta=451.2,466.2
XS Rating Curve= 0 ,0
Exp/Cntr=0.3,0.1

Type RM Length L Ch R = 1 ,1650.1  ,401.102,400,397.601
XS GIS Cut Line= 3
     1806660.738      372982.013     1806979.223      373315.837
      1807241.82      373686.033
#Sta/Elev= 30
       0 1012.13    29.4 1001.19    58.9  994.23    88.3  983.92     108  980.11
   137.4  969.82   157.1  965.43   186.5   955.3   206.1  947.71   255.2  919.35
   284.7  904.36   353.4  895.59   422.1  889.71   453.9  881.49   461.4  880.94
   468.9  881.36     500  888.75   538.6  894.66   577.3  898.41   596.6  904.27
   615.9  907.89   654.5  921.81   722.1   935.7   751.1  943.62   780.1  945.67
     809   951.5     838  960.73   857.3  963.36   886.3  962.69   915.3  965.44
#Mann= 3 , 0 , 0
       0      .1       0   453.9    .045       0   468.9      .1       0
Bank Sta=453.9,468.9
XS Rating Curve= 0 ,0
Exp/Cntr=0.3,0.1

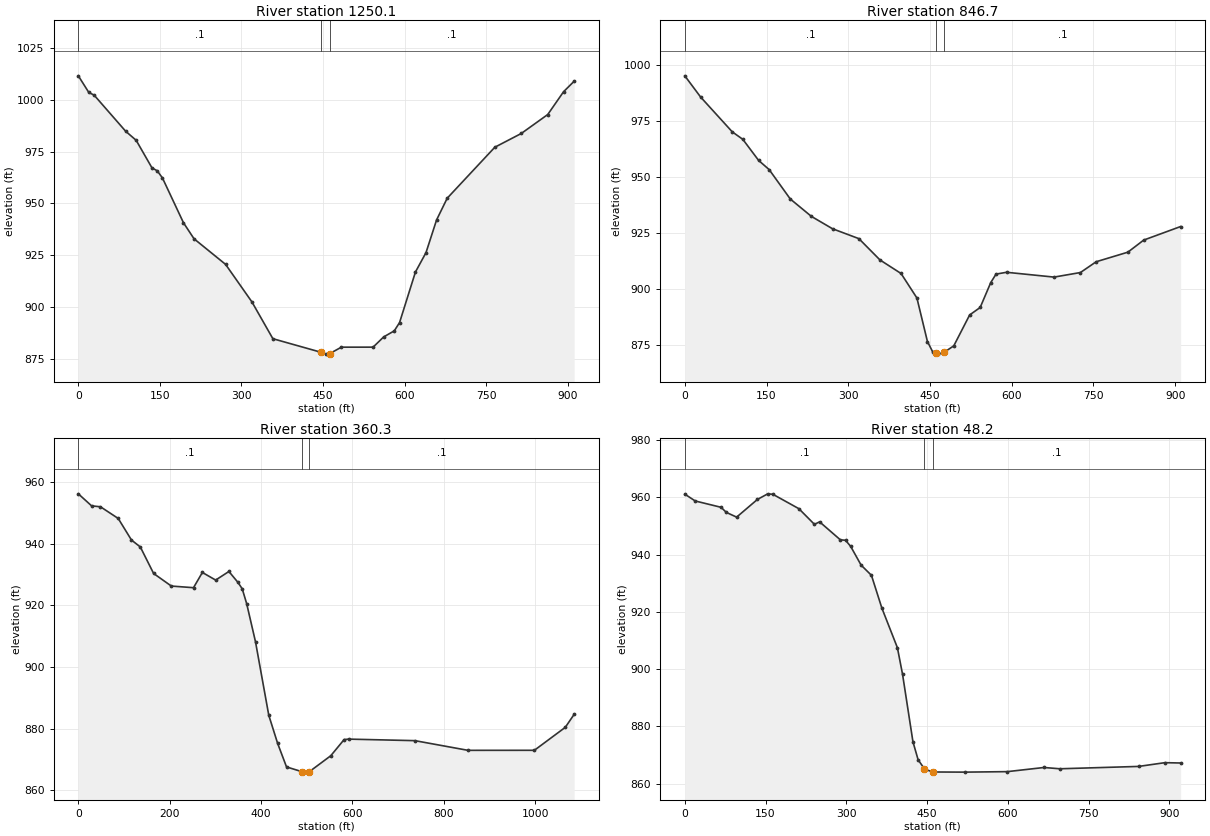
Type RM Length L Ch R = 1 ,1250.1  ,402.362,403.381,402.412
XS GIS Cut Line= 3
     1806349.764      373265.305     1806679.607      373578.079
     1806982.639      373920.644
#Sta/Elev= 30
       0 1011.61    19.3 1003.57      29 1002.31      87  984.87   106.4  980.47
   135.4  967.19   145.1  965.76   154.7  962.31   193.4  940.66   212.8  932.94
   270.8  920.59   319.2  902.49   357.8   884.7   447.1   878.1   454.6  877.26
   462.1  877.48   483.8  880.62   542.1  880.63   561.6  885.57   581.1   888.5
   590.8   892.5     620  916.91   639.4  926.25   658.9  942.06   678.4  952.52
     766  977.14   814.6  983.77   863.3  992.92   892.5 1003.96   911.9 1009.01
#Mann= 3 , 0 , 0
       0      .1       0   447.1    .045       0   462.1      .1       0
Bank Sta=447.1,462.1
XS Rating Curve= 0 ,0
Exp/Cntr=0.3,0.1

Type RM Length L Ch R = 1 ,846.7   ,484.343,486.367,488.246
XS GIS Cut Line= 3
     1806080.247      373534.074     1806397.141      373860.576
     1806714.034      374187.077
#Sta/Elev= 30
       0   995.3      29  985.83    87.1  970.26   106.5  966.91   135.5  957.49
   154.9  953.37   193.6  940.25   232.3  932.48   271.1  926.95   319.5  922.53
   358.2  913.01   396.9  906.95     426     896   445.3  876.55     455   871.9
   460.9   871.3   464.7  870.91   475.9  871.71   493.7  874.62   522.8  888.42
   542.1  891.76   561.5  902.87   571.2  906.67   590.5  907.49   677.7  905.34
   726.1  907.38   755.1  912.21   813.2  916.48   842.2  921.88     910  927.94
#Mann= 3 , 0 , 0
       0      .1       0   460.9    .045       0   475.9      .1       0
Bank Sta=460.9,475.9
XS Rating Curve= 0 ,0
Exp/Cntr=0.3,0.1

Type RM Length L Ch R = 1 ,360.3   ,309.371,312.196,311.924
XS GIS Cut Line= 3
     1805771.514       373855.57     1806151.329      374308.899
     1806604.658      374504.933
#Sta/Elev= 30
       0  956.21    29.1   952.3    48.5  952.01    87.3  948.22   116.3  941.22
   135.7  938.97   164.8  930.37   203.6  926.29   252.1  925.76   271.5   930.7
   300.6  928.23   329.6  931.02     349  927.55   358.7  925.42   368.4  920.62
   387.8  908.21   416.9  884.35   436.3  875.23   455.7  867.62   489.6  866.07
   494.5  865.93   504.6  865.96   552.6  871.25   581.7  876.48   591.4  876.64
   736.7  876.14   852.9     873   998.2  873.01  1065.9  880.46  1085.3  884.68
#Mann= 3 , 0 , 0
       0      .1       0   489.6    .045       0   504.6      .1       0
Bank Sta=489.6,504.6
XS Rating Curve= 0 ,0
Exp/Cntr=0.3,0.1

Type RM Length L Ch R = 1 ,48.2    ,57.823,48.153,41.726
XS GIS Cut Line= 3
     1805629.201      374059.829     1805868.241      374444.238
     1806168.827      374803.343
#Sta/Elev= 30
       0  961.09    19.3  958.71    67.4  956.49    77.1  954.72    96.3  953.06
   134.8  959.23   154.1   961.2   163.7  961.03   211.9  956.01   240.8  950.54
   250.4  951.42   288.9  945.14   298.6  944.98   308.2  942.82   327.5   936.3
   346.7  932.73     366  921.32   394.9  907.46   404.5  898.14   423.8  874.59
   433.4  868.31   445.2  865.12   460.2  864.05     521     864     599  864.17
   667.3  865.62   696.6  865.17   842.9  865.99   891.7   867.3     921  867.19
#Mann= 3 , 0 , 0
       0      .1       0   445.2    .045       0   460.2      .1       0
Bank Sta=445.2,460.2
XS Rating Curve= 0 ,0
Exp/Cntr=0.3,0.1

Chan Stop Cuts=-1
Use User Specified Reach Order=0